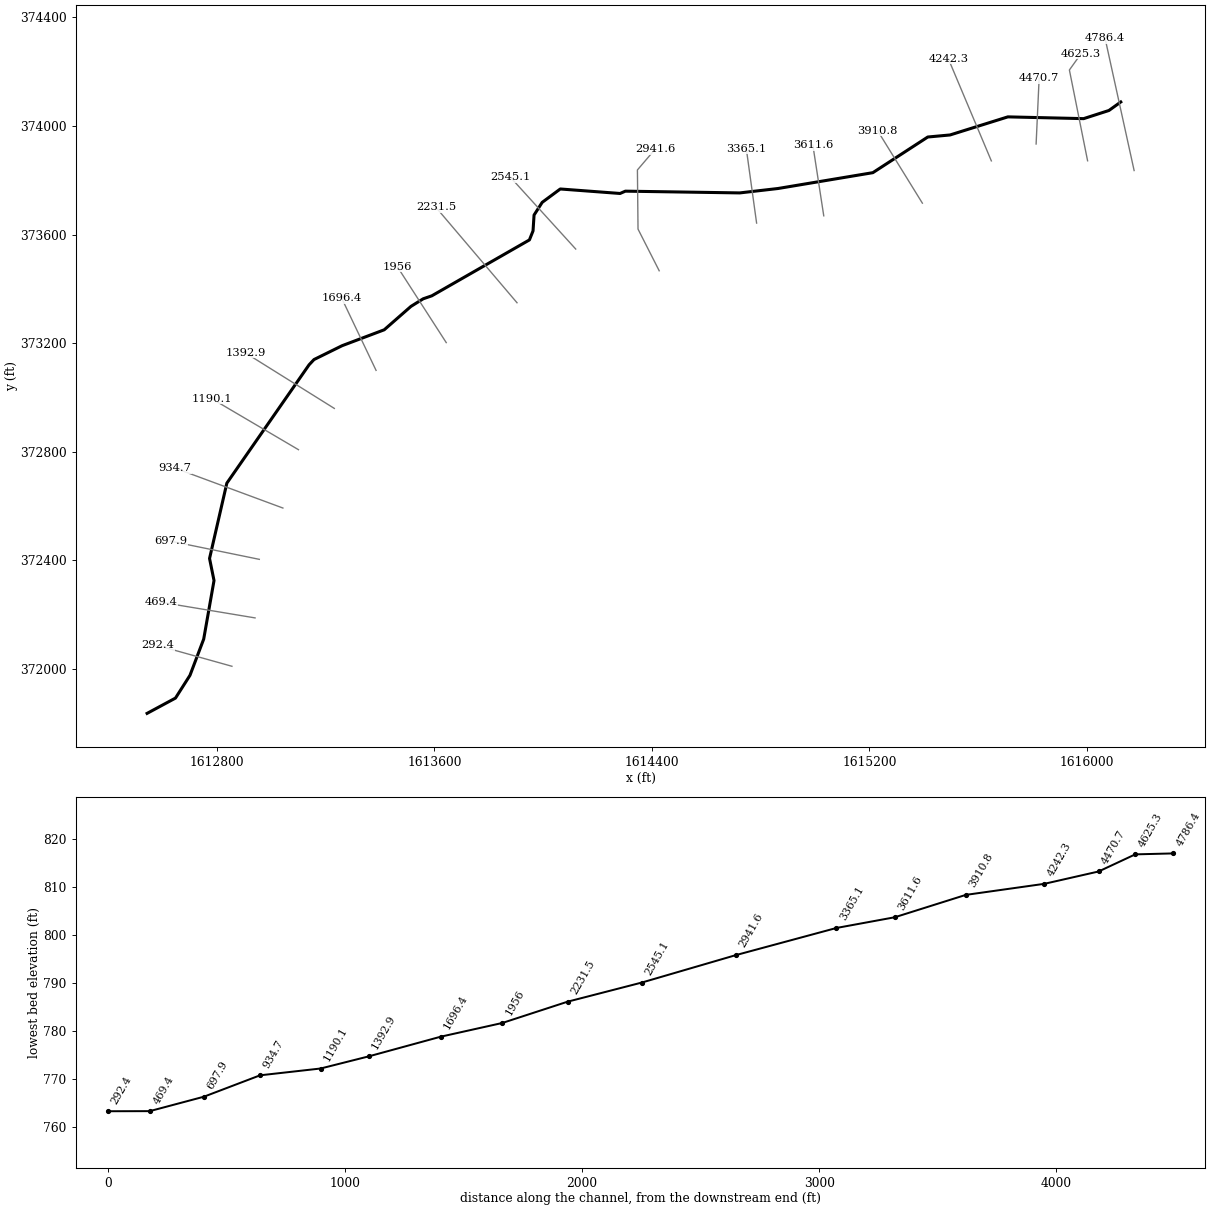
--- ROLLEMFK.prj (project) ---

Proj Title=ROLLEMFK
Current Plan=p01
Default Exp/Contr=0,0
English Units
Geom File=g01
Flow File=f01
Plan File=p01
BEGIN DESCRIPTION:
END DESCRIPTION:
DSS Export Rating Curves= 0
DSS Export Rating Curve Sorted= 0
DSS Export Volume Flow Curves= 0
DXF OffsetX= 0
DXF OffsetY= 0
DXF ScaleX= 0
DXF ScaleY= 0

--- ROLLEMFK.p01 (plan) ---

Plan Title=Floodplain
Program Version=4.00
Geom File=g01
Flow File=f01
K Sum by GR=0
Std Step Tol=0.01
Critical Tol=0.01
Num of Std Step Trials=20
Max Error Tol=0.3
Flow Tol Ratio=0.001
Split Flow NTrial=30
Split Flow Tol=0.02
Split Flow Ratio=0.02
Log Output Level=0
Friction Slope Method=1
Unsteady Friction Slope Method=2
Unsteady Bridges Friction Slope Method=1
Global Log Level=0
CheckData=False
Run HTab=0
Run UNet=0
Run PostProcess=0
UNET Theta=0
UNET Theta Warmup=0
UNET ZTol=0
UNET ZSATol=0
UNET MxIter=0
UNET MaxInSteps=0
UNET DtIC=0
UNET DtMin=0
UNET MaxCRTS=0
UNET WFStab=0
UNET SFStab=0
UNET WFX=0
UNET SFX=0
UNET DSS MLevel=0
UNET DZMax Abort=0
UNET Convert EG Bridges=0
UNET Use Existing IB Tables=0
UNET Froude Limit=0
UNET Froude Power=0
Write IC File=0
Echo Input=False
Echo Output=False
Write Detailed=0

--- ROLLEMFK.f01 (steady flow) ---

Flow Title=NFF Regression Equation
Program Version=4.00
Number of Profiles=1
Profile Names=P100yr
River Rch & RM=ROLLEMFK,Main      ,4786.4
502.8953
River Rch & RM=ROLLEMFK,Main      ,2941.6
542.7607
River Rch & RM=ROLLEMFK,Main      ,292.4
601.9317
Boundary for River Rch & Prof#=ROLLEMFK,Main      ,1
Up Type=0
Dn Type=3
Dn Slope=0.010652

--- ROLLEMFK.g01 (geometry) ---

Geom Title=Geometry
Program Version=4.00

River Reach=ROLLEMFK        ,Main
Reach XY= 30
     1616124.287      374088.483     1616080.698       374057.13
     1615987.729      374027.062     1615708.958      374033.573
     1615496.334      373966.889      1615414.46       373959.34
     1615212.449      373827.911     1614863.189      373769.499
     1614723.004      373753.308     1614302.183      373759.763
     1614282.712      373751.245     1614062.788      373767.797
     1613996.307      373718.498     1613966.372      373671.766
       1613962.6       373613.27     1613949.313      373580.053
     1613590.277      373373.995     1613558.637      373363.043
     1613513.611      373335.053     1613415.323      373248.811
     1613260.488      373190.238     1613157.049      373139.127
     1613138.795      373119.656     1612836.444      372683.552
     1612772.842      372405.928      1612789.29      372324.575
     1612751.351      372108.847     1612700.837      371975.213
     1612647.558      371891.371      1612543.11      371835.011

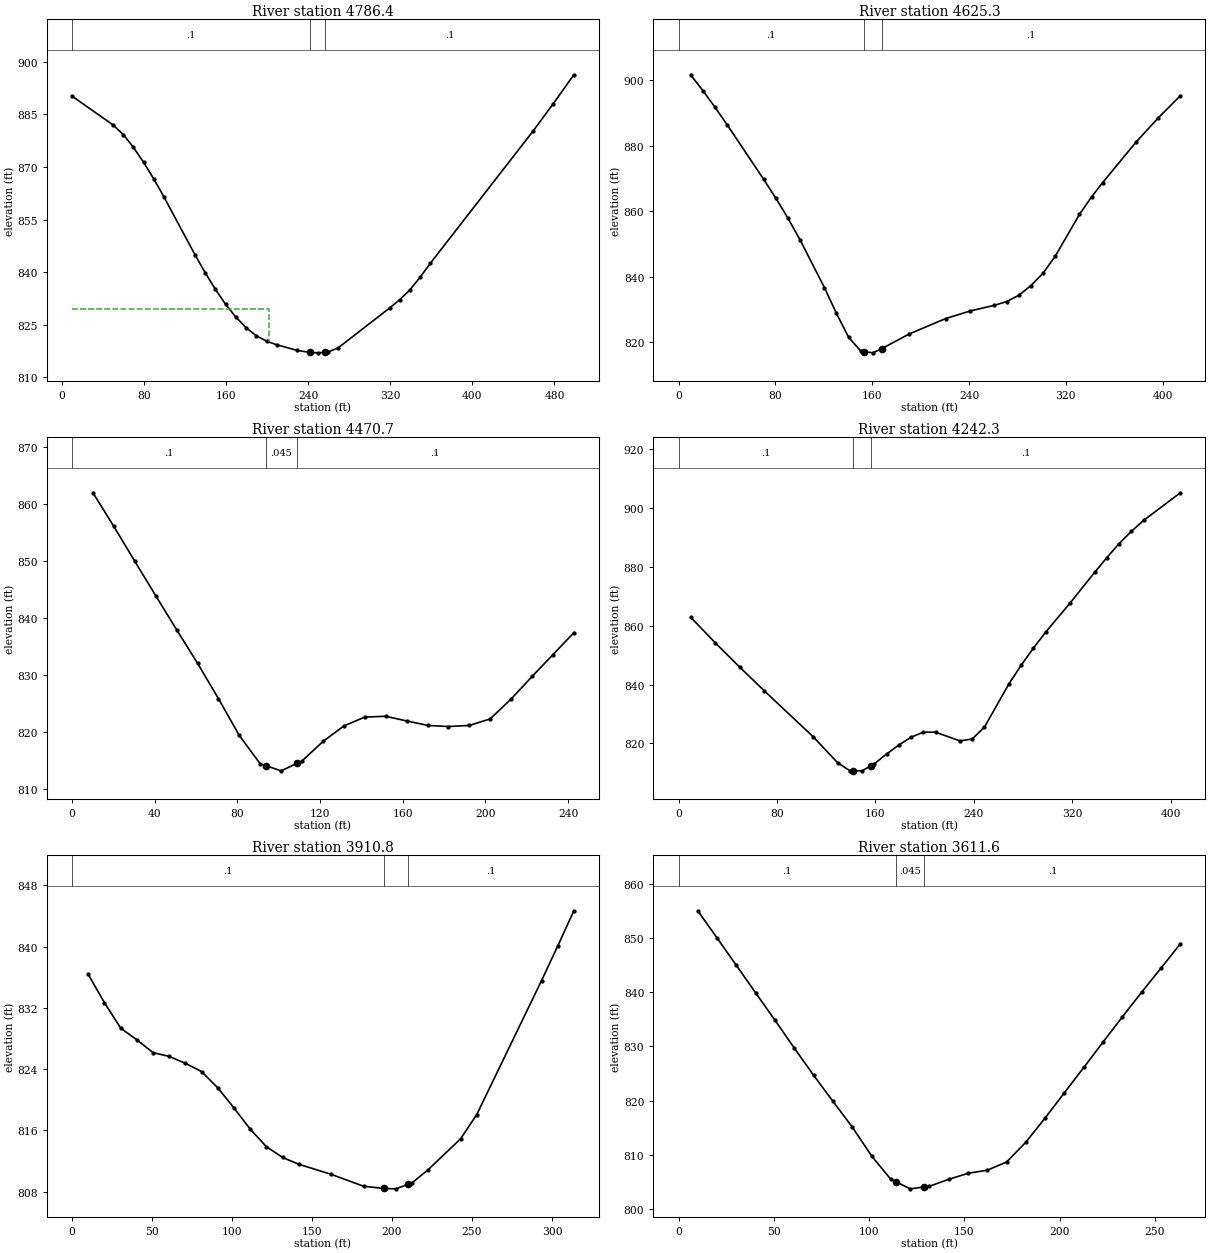
Type RM Length L Ch R = 1 ,4786.4  ,161,161.1,161.1
XS GIS Cut Line= 2
     1616173.368      373835.729     1616066.561      374323.037
#Sta/Elev= 30
      10  890.22    49.9  882.01    59.9  879.27    69.8  875.62    79.8   871.3
    89.8  866.53    99.8  861.33   129.7  845.03   139.7  839.87   149.7  835.12
   159.6  830.85   169.6  827.22   179.6  824.19   189.6  821.88   199.6  820.34
   209.5  819.33   229.5  817.71   241.9  817.15   249.4  817.03   256.9   817.2
   259.4  817.25   269.4  818.49   319.3  829.79   329.3   832.2   339.2     835
   349.2  838.61   359.2  842.62     459   880.2   478.9  888.09   498.9  896.31
#Mann= 3 , 0 , 0
      10      .1       0   241.9    .045       0   256.9      .1       0
#XS Ineff= 2 , 0
          202.18  829.52
Permanent Ineff=
       F       F
Bank Sta=241.9,256.9
XS Rating Curve= 0 ,0
Exp/Cntr=0.3,0.1

Type RM Length L Ch R = 1 ,4625.3  ,160.1,154.6,149.1
XS GIS Cut Line= 3
     1616002.239      373871.721     1615935.308      374206.378
       1615977.9      374266.007
#Sta/Elev= 30
      10  901.67    20.1  896.85    30.1  891.78    40.2  886.41    70.3  869.79
    80.3  864.08    90.3  857.99   100.4  851.31   120.5  836.76   130.5  828.84
   140.5  821.61   150.6  817.36   153.1  817.22   160.6  816.83   168.1  818.15
   190.7   822.6   220.8   827.3   240.9  829.59     261  831.34     271  832.46
   281.1  834.39   291.1  837.32   301.1  841.09   311.2  846.28   331.2  859.04
   341.3  864.45   350.4  868.77   377.9  881.08   396.2  888.47   414.6  895.27
#Mann= 3 , 0 , 0
       0      .1       0   153.1    .045       0   168.1      .1       0
Bank Sta=153.1,168.1
XS Rating Curve= 0 ,0
Exp/Cntr=0.3,0.1

Type RM Length L Ch R = 1 ,4470.7  ,218.5,228.5,238.5
XS GIS Cut Line= 2
     1615812.894      373933.636      1615824.02      374176.177
#Sta/Elev= 26
    10.1  861.96    20.2  856.07    30.3     850    40.5  843.92    50.6  837.97
    60.7  832.11    70.8  825.92    80.9  819.47      91   814.5    93.7  814.17
   101.2  813.26   108.7  814.56   111.3  815.01   121.4   818.4   131.5  821.12
   141.6  822.67   151.7  822.82   161.9     822     172  821.22   182.1  821.02
   192.2  821.21   202.3  822.35   212.4  825.83   222.6  829.79   232.7  833.62
   242.8  837.46
#Mann= 3 , 0 , 0
       0      .1       0    93.7    .045       0   108.7      .1       0
Bank Sta=93.7,108.7
XS Rating Curve= 0 ,0
Exp/Cntr=0.3,0.1

Type RM Length L Ch R = 1 ,4242.3  ,328,331.5,335
XS GIS Cut Line= 2
     1615648.233      373871.332     1615490.248      374247.382
#Sta/Elev= 30
     9.9  862.85    29.8  854.18    49.7  845.92    69.6  837.91   109.4  822.29
   129.3  813.45   139.3  810.73   141.7  810.72   149.2  810.69   156.7  812.49
   159.2   813.1   169.1   816.4   179.1  819.47     189  822.09     199  823.83
   208.9   823.8   228.8  820.86   238.8  821.51   248.7  825.56   268.6  840.25
   278.6   846.6   288.5  852.37   298.5  857.83   318.4  867.73   338.2  878.07
   348.2  883.11   358.1  887.85   368.1  892.01     378  895.73   407.9  905.12
#Mann= 3 , 0 , 0
       0      .1       0   141.7    .045       0   156.7      .1       0
Bank Sta=141.7,156.7
XS Rating Curve= 0 ,0
Exp/Cntr=0.3,0.1

Type RM Length L Ch R = 1 ,3910.8  ,308.3,299.2,290
XS GIS Cut Line= 2
     1615394.567      373715.571     1615229.906      373982.589
#Sta/Elev= 26
    10.1  836.37    20.2  832.69    30.4  829.35    40.5  827.83    50.6  826.16
    60.7  825.66    70.8  824.77      81  823.68    91.1  821.56   101.2  818.94
   111.3  816.19   121.4   813.9   131.6  812.48   141.7  811.59   161.9  810.28
   182.2  808.72   194.9  808.43   202.4  808.38   209.9  808.95   212.5  809.15
   222.6  810.88   242.9  814.91     253  818.08   293.5  835.56   303.6  840.06
   313.7  844.67
#Mann= 3 , 0 , 0
       0      .1       0   194.9    .045       0   209.9      .1       0
Bank Sta=194.9,209.9
XS Rating Curve= 0 ,0
Exp/Cntr=0.3,0.1

Type RM Length L Ch R = 1 ,3611.6  ,247.1,246.5,246.2
XS GIS Cut Line= 2
     1615031.867      373668.843     1614991.815      373929.186
#Sta/Elev= 28
    10.1  855.02    20.3  849.97    30.4  844.93    40.5  839.87    50.7  834.79
    60.8  829.68    70.9  824.67      81  819.89    91.2  815.12   101.3  809.81
   111.4  805.49   114.1  805.02   121.6  803.72   129.1  804.08   131.7   804.2
   141.8  805.47     152  806.59   162.1  807.16   172.2  808.67   182.4  812.35
   192.5  816.83   202.6  821.47   212.8  826.14   222.9  830.83     233  835.46
   243.1     840   253.3  844.46   263.4  848.92
#Mann= 3 , 0 , 0
       0      .1       0   114.1    .045       0   129.1      .1       0
Bank Sta=114.1,129.1
XS Rating Curve= 0 ,0
Exp/Cntr=0.3,0.1

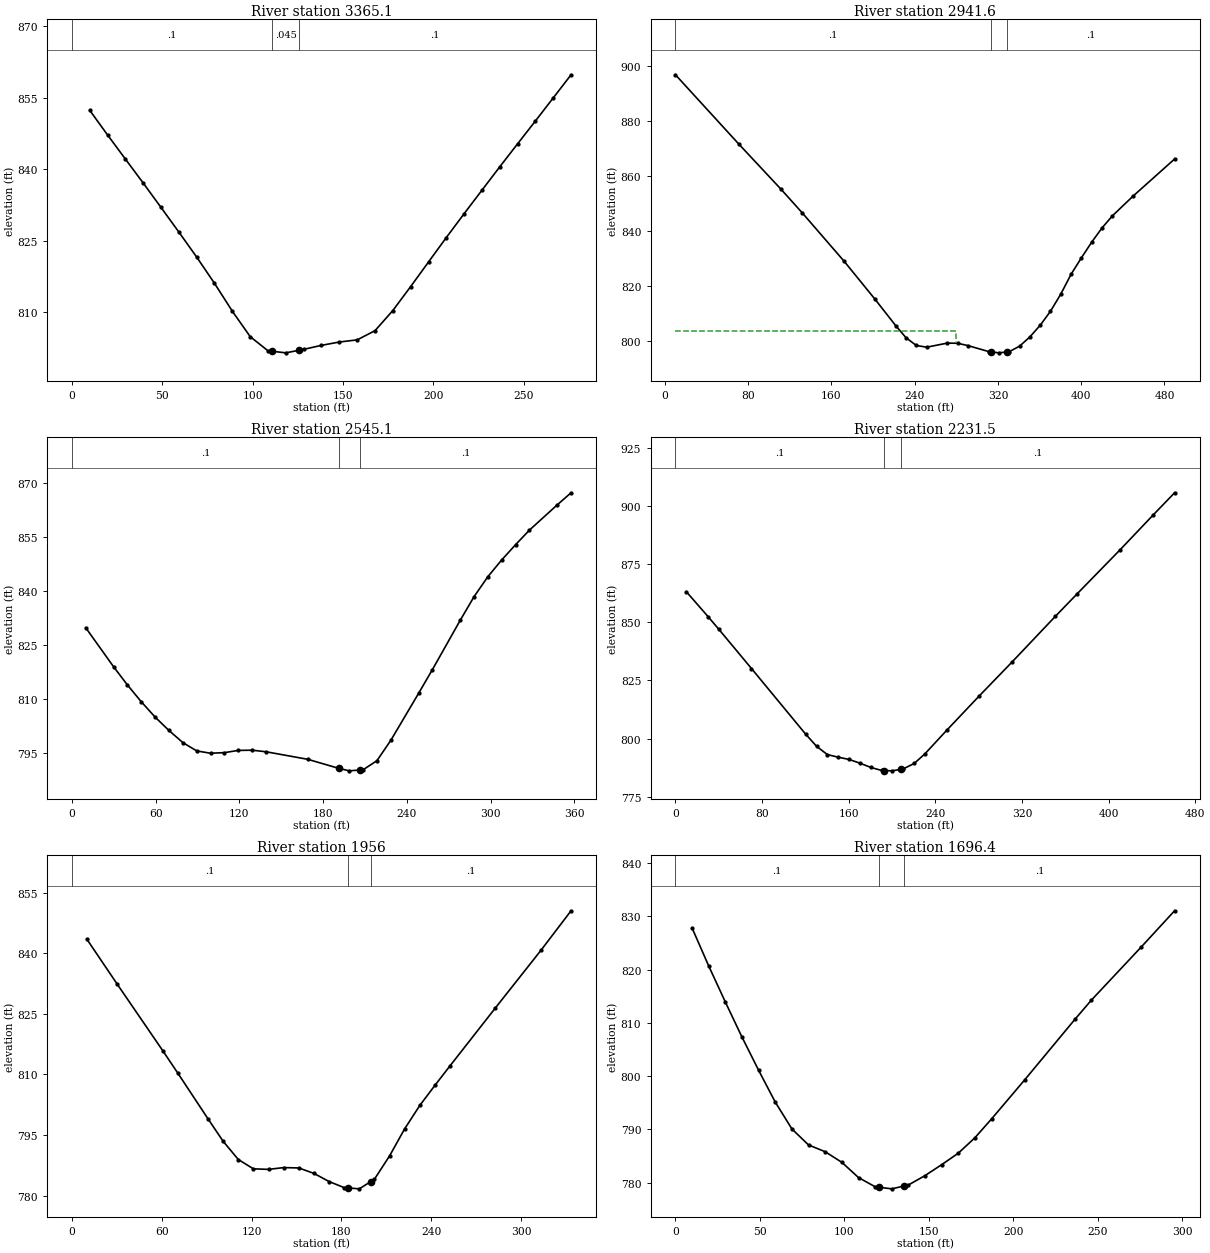
Type RM Length L Ch R = 1 ,3365.1  ,444.3,423.5,443.9
XS GIS Cut Line= 2
     1614784.876      373642.142     1614747.048      373915.835
#Sta/Elev= 30
     9.9  852.35    19.7  847.21    29.6  842.14    39.5  837.09    49.3     832
    59.2  826.82    69.1  821.55    78.9  816.08    88.8  810.21    98.7  804.87
   108.5  801.92   110.9  801.81   118.4  801.48   125.9  802.03   128.3  802.21
   138.1  803.05     148  803.75   157.9   804.2   167.8  806.14   177.6  810.34
   187.5  815.38   197.4  820.55   207.2  825.65   217.1  830.68     227  835.62
   236.8   840.5   246.7  845.34   256.6  850.15   266.4  854.96   276.3  859.83
#Mann= 3 , 0 , 0
       0      .1       0   110.9    .045       0   125.9      .1       0
Bank Sta=110.9,125.9
XS Rating Curve= 0 ,0
Exp/Cntr=0.3,0.1

Type RM Length L Ch R = 1 ,2941.6  ,379.9,396.6,413.3
XS GIS Cut Line= 4
     1614426.627      373466.355     1614348.747       373619.89
     1614346.522      373837.955     1614411.051       373913.61
#Sta/Elev= 30
    10.1  896.65    70.9  871.55   111.4   855.2   131.7  846.68   172.2  829.02
   201.9  815.24   221.7   805.7   231.6  801.33   241.5   798.5   251.5  797.88
   271.3  799.36   281.2   799.3   291.1  798.46   310.9  796.31   313.3  796.19
   320.8  795.83   328.3  796.15   330.8  796.25   340.7  798.24   350.6  801.58
   360.5   805.8   370.4  810.89   380.3  817.09   390.2   824.3   400.2  830.31
   410.1  835.99   420.1  841.18     430  845.53   449.9  852.69   489.7  866.11
#Mann= 3 , 0 , 0
    10.1      .1       0   313.3    .045       0   328.3      .1       0
#XS Ineff= 2 , 0
          279.36  803.91
Permanent Ineff=
       F       F
Bank Sta=313.3,328.3
XS Rating Curve= 0 ,0
Exp/Cntr=0.3,0.1

Type RM Length L Ch R = 1 ,2545.1  ,314.4,313.6,312.8
XS GIS Cut Line= 2
     1614119.557       373546.46     1613879.241      373811.253
#Sta/Elev= 30
     9.9  829.88    29.8  819.06    39.7  814.01    49.7   809.3    59.6  805.05
    69.5  801.33    79.5  797.95    89.4  795.65    99.3     795   109.3  795.17
   119.2  795.79   129.1  795.85   139.1  795.41   168.9  793.32   191.2   790.8
   198.7  790.11   206.2  790.34   208.6  790.41   218.5  792.92   228.5  798.61
   248.3  811.61   258.3  818.27   278.1   831.9   288.1  838.52     298  844.08
   307.9  848.73   317.9  852.99   327.8  857.03   347.7  864.04   357.6   867.4
#Mann= 3 , 0 , 0
       0      .1       0   191.2    .045       0   206.2      .1       0
Bank Sta=191.2,206.2
XS Rating Curve= 0 ,0
Exp/Cntr=0.3,0.1

Type RM Length L Ch R = 1 ,2231.5  ,278.7,275.5,272.3
XS GIS Cut Line= 2
     1613903.717      373348.422     1613605.547      373699.995
#Sta/Elev= 26
      10  863.25    30.1   852.5    40.1  847.02    70.2  830.16   120.3  801.87
   130.3  796.69   140.3   793.1   150.3  791.99   160.3  791.02   170.4   789.4
   180.4  787.58   190.4  786.28   192.9  786.24   200.4  786.11   207.9  786.76
   210.5  786.98   220.5  789.29   230.5  793.47   250.5  803.56   280.6  818.37
   310.7  832.87   350.8  852.58   370.8  862.22   410.9  881.38   440.9   896.1
     461  905.81
#Mann= 3 , 0 , 0
       0      .1       0   192.9    .045       0   207.9      .1       0
Bank Sta=192.9,207.9
XS Rating Curve= 0 ,0
Exp/Cntr=0.3,0.1

Type RM Length L Ch R = 1 ,1956    ,262.5,259.6,256.8
XS GIS Cut Line= 2
     1613643.375      373201.562     1613463.138      373481.931
#Sta/Elev= 26
    10.1   843.4    30.3  832.31    60.6   815.9    70.7  810.32    90.9  798.98
     101  793.43   111.1  788.93   121.2  786.62   131.3  786.49   141.4  786.93
   151.5  786.84   161.6  785.49   171.7  783.48   181.8  781.97   184.4   781.9
   191.9  781.67   199.4  783.43     202  784.05   212.1  789.82   222.2  796.54
   232.3  802.32   242.4  807.29   252.5  812.13   282.8  826.47   313.1  840.68
   333.3  850.51
#Mann= 3 , 0 , 0
       0      .1       0   184.4    .045       0   199.4      .1       0
Bank Sta=184.4,199.4
XS Rating Curve= 0 ,0
Exp/Cntr=0.3,0.1

Type RM Length L Ch R = 1 ,1696.4  ,290.7,303.5,316.3
XS GIS Cut Line= 2
     1613385.258      373099.205     1613258.424      373366.223
#Sta/Elev= 26
     9.9  827.79    19.7  820.69    29.6  813.88    39.4  807.33    49.3  801.06
    59.1  795.11      69  790.05    78.8  787.06    88.7  785.78    98.5   783.8
   108.4  780.93   118.2  779.21   120.6  779.11   128.1  778.81   135.6  779.36
     138  779.54   147.8   781.3   157.7  783.36   167.5  785.51   177.4  788.43
   187.2  791.95   206.9  799.32   236.5  810.64   246.3  814.27   275.9  824.28
   295.6  831.07
#Mann= 3 , 0 , 0
       0      .1       0   120.6    .045       0   135.6      .1       0
Bank Sta=120.6,135.6
XS Rating Curve= 0 ,0
Exp/Cntr=0.3,0.1

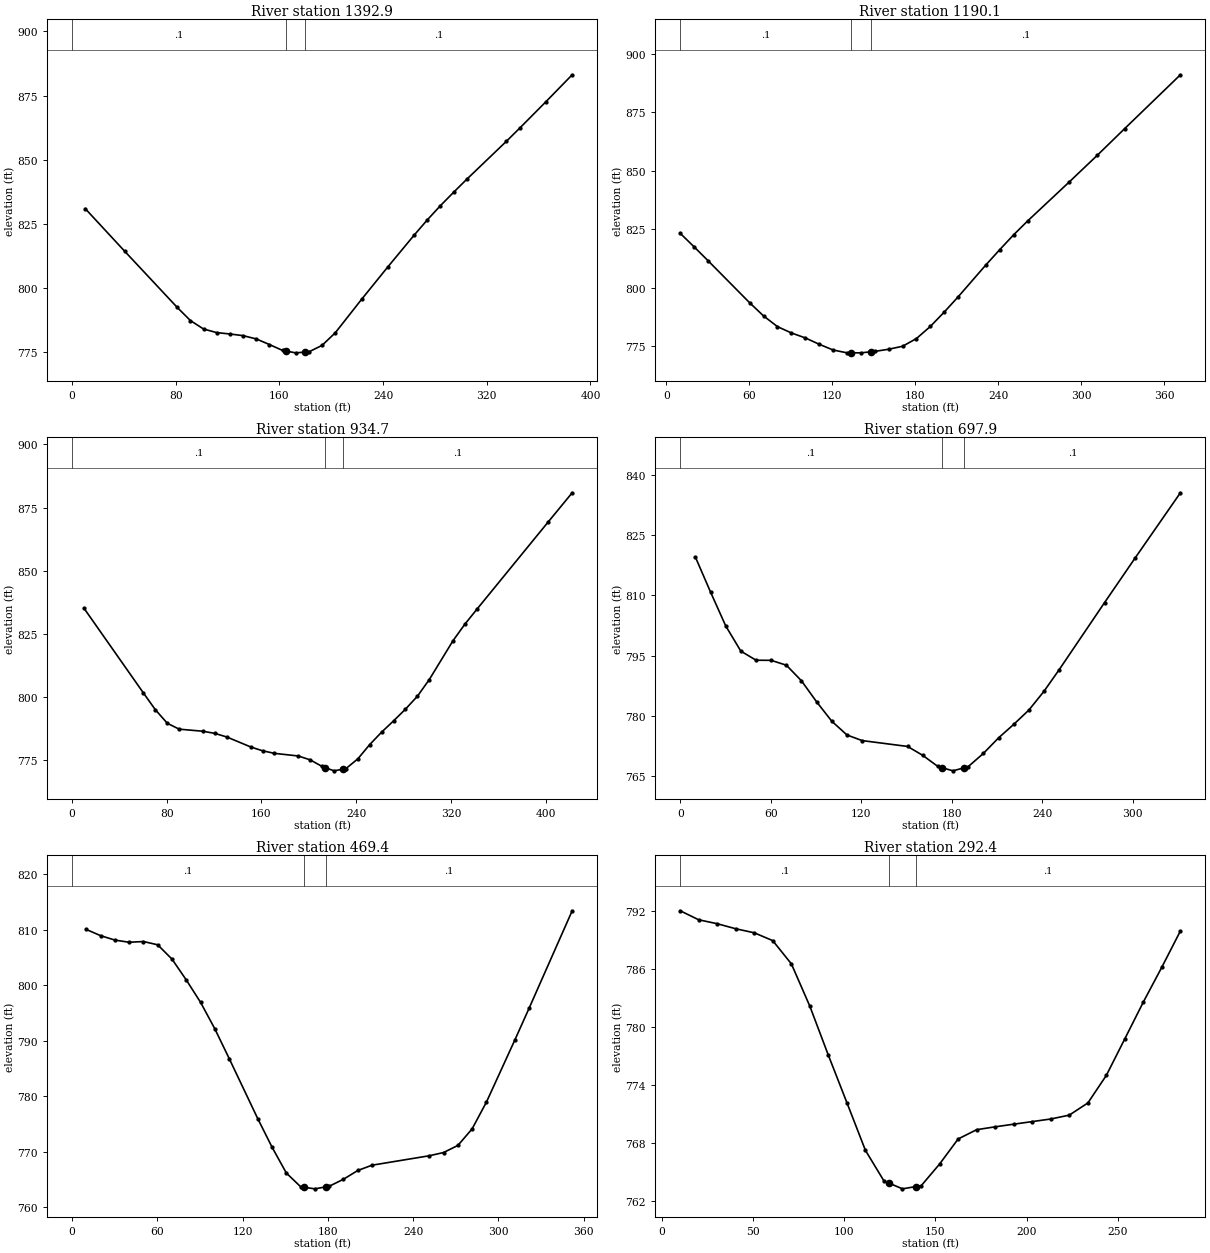
Type RM Length L Ch R = 1 ,1392.9  ,202.2,202.8,203.4
XS GIS Cut Line= 2
     1613231.723      372959.021     1612904.626      373163.735
#Sta/Elev= 28
    10.2  830.94    40.6  814.35    81.2  792.42    91.4  787.28   101.5     784
   111.7  782.59   121.9  782.06     132  781.41   142.2  780.13   152.3  777.95
   162.5  775.64   165.1   775.4   172.6  774.71   180.1     775   182.8   775.1
   192.9  777.61   203.1  782.51   223.4  795.55   243.7  808.23     264  820.61
   274.2  826.58   284.3  832.12   294.5  837.34   304.6   842.4   335.1  857.16
   345.3  862.26   365.6  872.59   385.9  883.12
#Mann= 3 , 0 , 0
       0      .1       0   165.1    .045       0   180.1      .1       0
Bank Sta=165.1,180.1
XS Rating Curve= 0 ,0
Exp/Cntr=0.3,0.1

Type RM Length L Ch R = 1 ,1190.1  ,251.3,255.4,259.5
XS GIS Cut Line= 2
     1613099.853      372806.905       1612779.8      372995.529
#Sta/Elev= 29
      10  823.26    20.1  817.46    30.1  811.57    60.2  793.57    70.3  787.92
    80.3  783.38    90.4  780.67   100.4  778.56   110.4  775.86   120.5  773.39
   130.5  772.19   133.1  772.19   140.6  772.18   148.1  772.65   150.6   772.8
   160.6  773.71   170.7  774.99   180.7  778.28   190.8  783.47   200.8   789.6
   210.9  796.14   230.9  809.75     241  816.33     251  822.65   261.1  828.56
   291.2  845.24   311.3  856.55   331.3  868.07   371.5  891.04
#Mann= 3 , 0 , 0
      10      .1       0   133.1    .045       0   148.1      .1       0
Bank Sta=133.1,148.1
XS Rating Curve= 0 ,0
Exp/Cntr=0.3,0.1

Type RM Length L Ch R = 1 ,934.7   ,233.3,236.8,240.2
XS GIS Cut Line= 2
     1613042.585      372591.872     1612646.509      372738.731
#Sta/Elev= 30
    10.1  835.14    60.3   801.6    70.4  794.95    80.5  789.59    90.5  787.26
   110.6  786.43   120.7  785.58   130.8  784.15   150.9  780.22   160.9   778.7
     171  777.68   191.1  776.64   201.2   775.1   211.2  772.49   213.8  772.04
   221.3  770.76   228.8  771.41   231.3  771.63   241.4  775.51   251.4  781.14
   261.5  786.09   271.6  790.55   281.6  795.17   291.7  800.29   301.7  806.87
   321.8   822.3   331.9  828.89     342  834.76   402.3  869.37   422.4  880.83
#Mann= 3 , 0 , 0
       0      .1       0   213.8    .045       0   228.8      .1       0
Bank Sta=213.8,228.8
XS Rating Curve= 0 ,0
Exp/Cntr=0.3,0.1

Type RM Length L Ch R = 1 ,697.9   ,227.5,228.5,229.5
XS GIS Cut Line= 2
     1612955.804      372402.734     1612630.933      372469.489
#Sta/Elev= 28
    10.1  819.47    20.1   810.8    30.2  802.35    40.2  796.09    50.3  793.83
    60.3   793.8    70.4  792.59    80.4  788.71    90.5  783.45   100.5  778.65
   110.6  775.22   120.6  773.83   150.8  772.37   160.8  770.16   170.9  767.38
   173.4  767.11   180.9   766.3   188.4  767.08     191  767.35     201  770.62
   211.1   774.5   221.1  777.84   231.2  781.42   241.2  786.08   251.3  791.47
   281.4  808.17   301.5  819.18   331.7   835.5
#Mann= 3 , 0 , 0
       0      .1       0   173.4    .045       0   188.4      .1       0
Bank Sta=173.4,188.4
XS Rating Curve= 0 ,0
Exp/Cntr=0.3,0.1

Type RM Length L Ch R = 1 ,469.4   ,179.4,177,174.6
XS GIS Cut Line= 2
     1612940.228      372186.895     1612593.105      372244.749
#Sta/Elev= 30
    10.1  810.01    20.1   808.9    30.2   808.1    40.2  807.71    50.3  807.84
    60.3  807.25    70.4  804.66    80.4  800.92    90.5  796.87   100.5  792.11
   110.6  786.76   130.7  775.93   140.8  770.77   150.8  766.14   160.9  763.66
   163.4  763.57   170.9  763.29   178.4  763.64     181  763.76     191  765.02
   201.1   766.6   211.1  767.55   251.4  769.25   261.4  769.83   271.5  771.11
   281.5  774.09   291.6  778.93   311.7  790.18   321.7  795.89   351.9  813.38
#Mann= 3 , 0 , 0
       0      .1       0   163.4    .045       0   178.4      .1       0
Bank Sta=163.4,178.4
XS Rating Curve= 0 ,0
Exp/Cntr=0.3,0.1

Type RM Length L Ch R = 1 ,292.4   ,310.8,292.4,274
XS GIS Cut Line= 2
      1612855.25      372008.596      1612581.44      372085.263
#Sta/Elev= 30
    10.2  792.05    20.3  791.12    30.5  790.71    40.6  790.19    50.8  789.77
    60.9  788.96    71.1  786.56    81.2  782.19    91.4  777.09   101.6  772.16
   111.7  767.25   121.9  764.07   124.5  763.87     132  763.27   139.5  763.51
   142.2  763.58   152.3  765.83   162.5  768.43   172.6  769.39   182.8  769.69
   192.9  769.96   203.1  770.23   213.3   770.5   223.4   770.9   233.6  772.16
   243.7  775.01   253.9  778.82     264  782.61   274.2  786.24   284.3  789.96
#Mann= 3 , 0 , 0
    10.2      .1       0   124.5    .045       0   139.5      .1       0
Bank Sta=124.5,139.5
XS Rating Curve= 0 ,0
Exp/Cntr=0.3,0.1

Chan Stop Cuts=-1
Use User Specified Reach Order=0